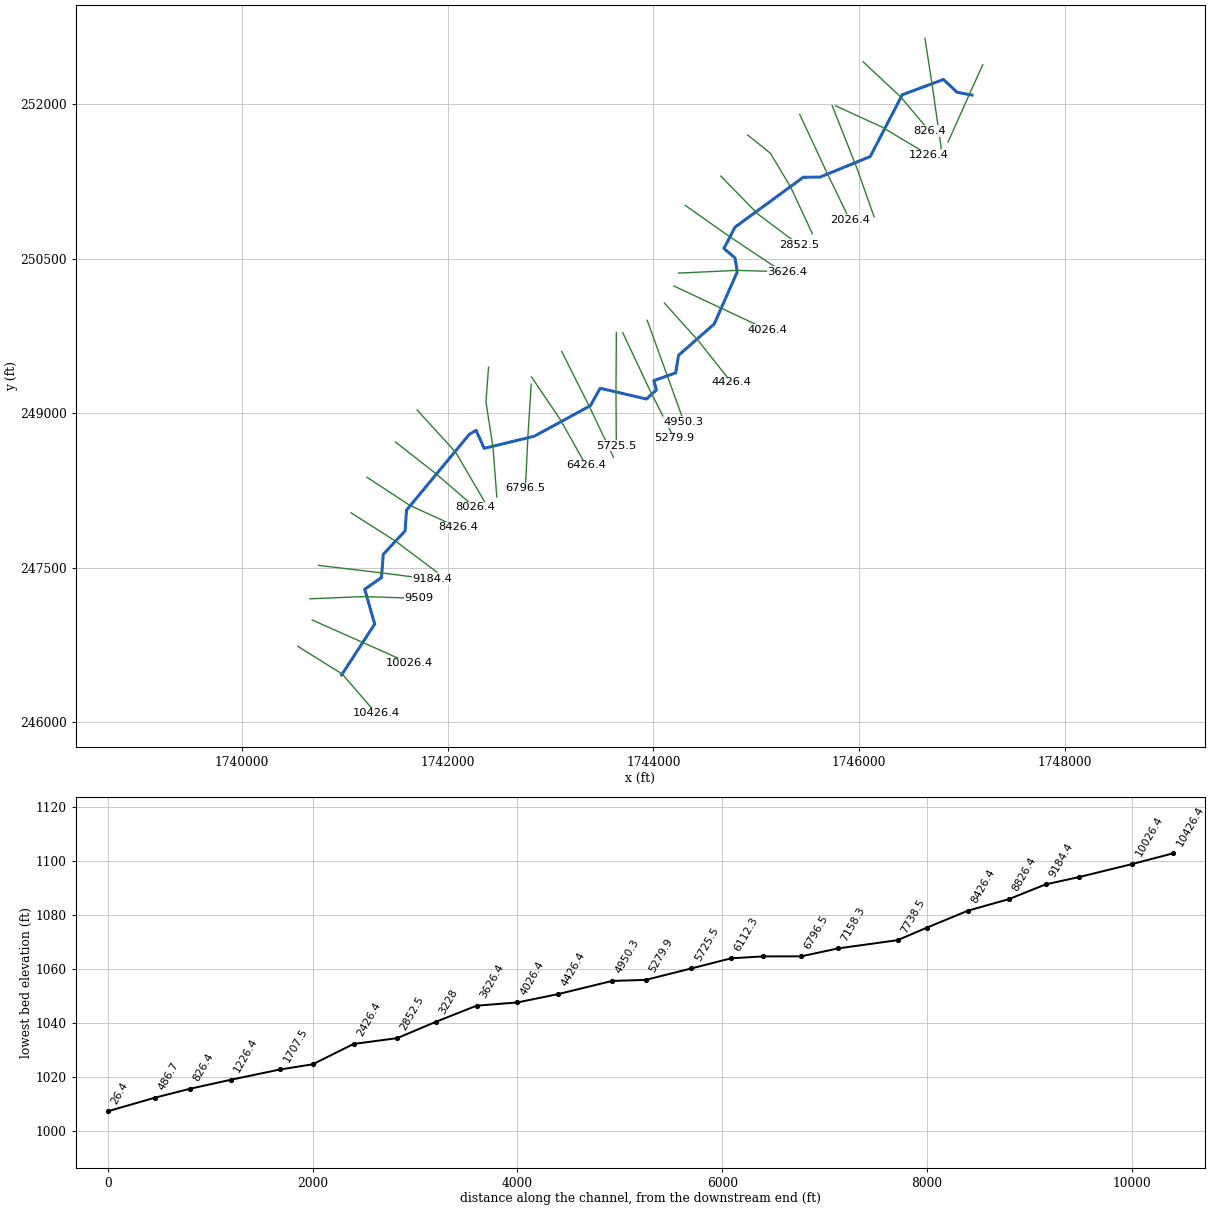
--- HastingRn.prj (project) ---

Proj Title=HastingRn
Current Plan=p01
Default Exp/Contr=0,0
English Units
Geom File=g01
Flow File=f01
Plan File=p01
BEGIN DESCRIPTION:
END DESCRIPTION:
DSS Export Rating Curves= 0
DSS Export Rating Curve Sorted= 0
DSS Export Volume Flow Curves= 0
DXF OffsetX= 0
DXF OffsetY= 0
DXF ScaleX= 0
DXF ScaleY= 0

--- HastingRn.p01 (plan) ---

Plan Title=Floodplain
Program Version=4.00
Geom File=g01
Flow File=f01
K Sum by GR=0
Std Step Tol=0.01
Critical Tol=0.01
Num of Std Step Trials=20
Max Error Tol=0.3
Flow Tol Ratio=0.001
Split Flow NTrial=30
Split Flow Tol=0.02
Split Flow Ratio=0.02
Log Output Level=0
Friction Slope Method=1
Unsteady Friction Slope Method=2
Unsteady Bridges Friction Slope Method=1
Global Log Level=0
CheckData=False
Run HTab=0
Run UNet=0
Run PostProcess=0
UNET Theta=0
UNET Theta Warmup=0
UNET ZTol=0
UNET ZSATol=0
UNET MxIter=0
UNET MaxInSteps=0
UNET DtIC=0
UNET DtMin=0
UNET MaxCRTS=0
UNET WFStab=0
UNET SFStab=0
UNET WFX=0
UNET SFX=0
UNET DSS MLevel=0
UNET DZMax Abort=0
UNET Convert EG Bridges=0
UNET Use Existing IB Tables=0
UNET Froude Limit=0
UNET Froude Power=0
Write IC File=0
Echo Input=False
Echo Output=False
Write Detailed=0

--- HastingRn.f01 (steady flow) ---

Flow Title=NFF Regression Equation
Program Version=4.00
Number of Profiles= 1
Profile Names=P100yr
River Rch & RM=HastingRn,Main            ,10426.4
743.2307
River Rch & RM=HastingRn,Main            ,8826.4
772.2763
River Rch & RM=HastingRn,Main            ,8426.4
958.0579
River Rch & RM=HastingRn,Main            ,6112.3
1063.697
River Rch & RM=HastingRn,Main            ,2426.4
1174.942
River Rch & RM=HastingRn,Main            ,26.4
1296.729
River Rch & RM=HastingRn,Main            ,26.4
1296.729
Boundary for River Rch & Prof#=HastingRn,Main            , 1
Up Type= 0
Dn Type= 3
Dn Slope=0.00971
DSS Import GetInterval= 0
DSS Import GetPeak= 0
DSS Import FillOption= 0

--- HastingRn.g01 (geometry) ---

Geom Title=USGS 3m DEM
Program Version=4.00

River Reach=HastingRn     ,Main
Reach XY= 30
     1740968.812      246458.821     1741290.307      246953.079
     1741192.916      247290.570     1741355.969      247404.494
     1741373.426      247630.069     1741585.625      247857.760
     1741599.399      248058.880     1742210.397      248795.918
     1742275.780      248833.878     1742354.665      248659.324
     1742841.357      248777.181     1743387.502      249074.300
     1743481.706      249243.221     1743931.490      249138.542
     1744028.409      249226.788     1744003.395      249317.285
     1744215.999      249392.478     1744243.737      249563.445
     1744590.749      249867.444     1744814.366      250373.768
     1744792.762      250509.476     1744684.676      250600.618
     1744792.553      250807.698     1745456.496      251292.470
     1745619.346      251294.132     1746107.194      251493.742
     1746418.620      252094.051     1746818.951      252242.121
     1746951.485      252117.906     1747096.090      252090.917

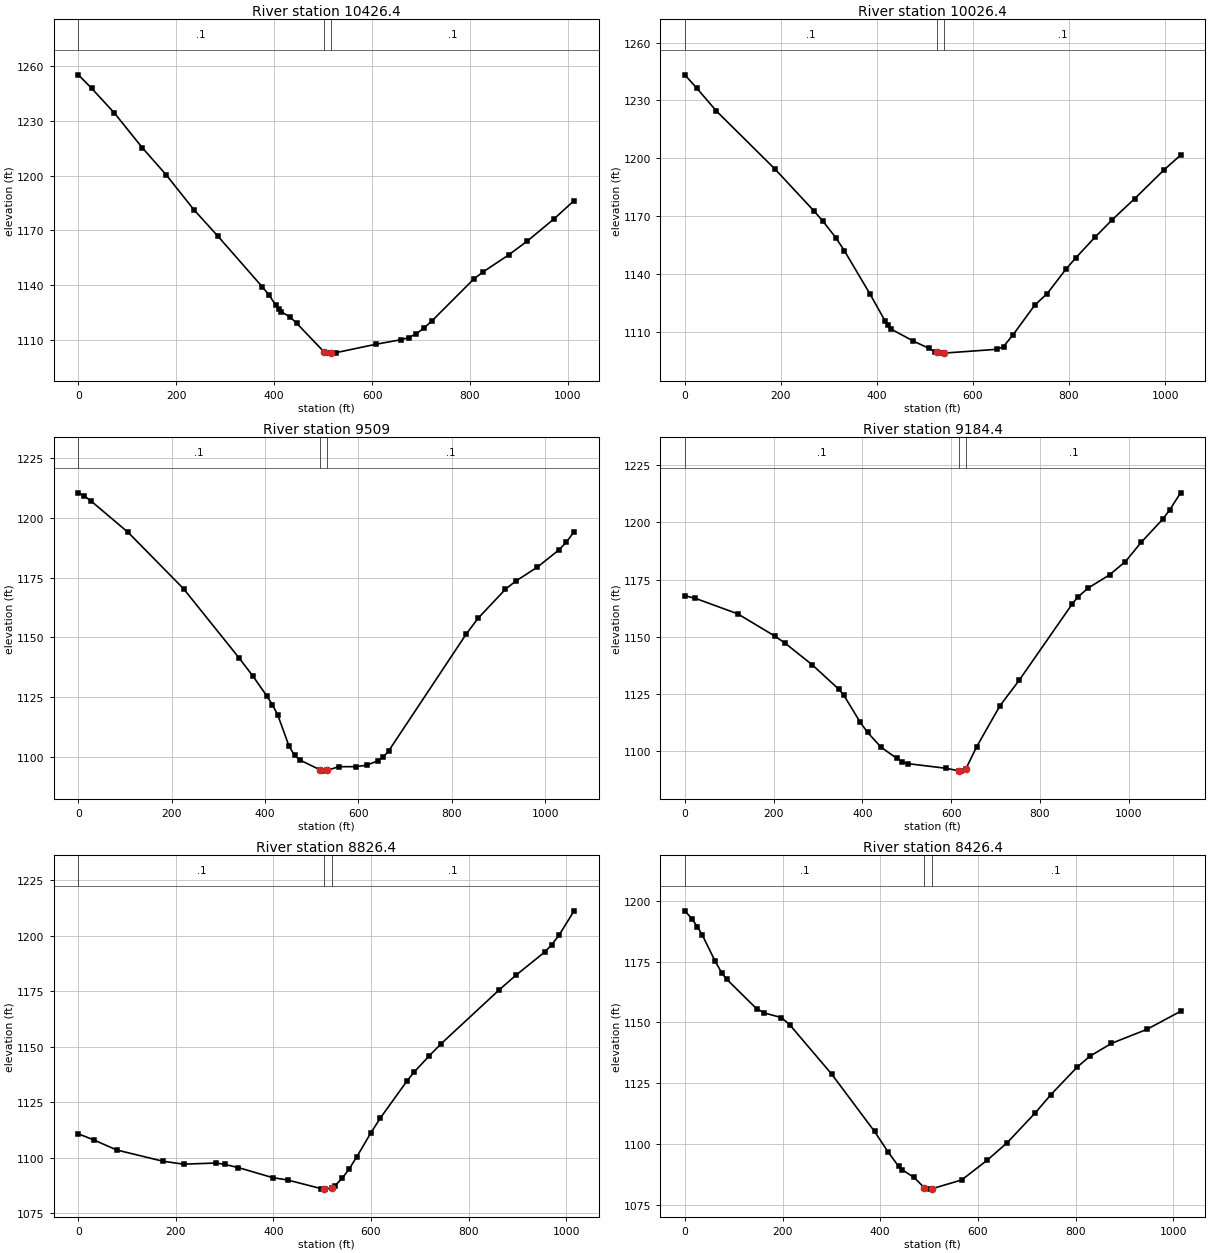
Type RM Length L Ch R = 1 ,10426.4,396.093,400,410.659
XS GIS Cut Line= 3
     1740543.566      246736.007     1740975.517      246466.241
     1741304.550      246085.135
#Sta/Elev= 30
       0 1255.14    27.0 1247.82    73.7 1234.23   130.4 1215.32   179.8 1200.29
   235.8 1181.40   285.5 1166.72   375.8 1139.10   388.9 1134.87   403.8 1128.93
   409.9 1126.81   414.7 1125.42   432.3 1122.66   445.7 1119.29   501.8 1103.53
   509.3 1102.84   516.8 1102.85   526.3 1103.09   608.5 1107.73   659.3 1110.19
   675.0 1111.35   690.7 1113.47   706.4 1116.69   722.0 1120.39   808.3 1143.54
   826.5 1147.23   878.9 1156.57   917.4 1164.22   971.9 1176.36  1012.8 1186.33
#Mann= 3 , 0 , 0
       0     0.1       0   501.8   0.045       0   516.8     0.1       0
Bank Sta=   501.8,   516.8
Exp/Cntr=0.3,0.1

Type RM Length L Ch R = 1 ,10026.4,507.161,517.413,526.481
XS GIS Cut Line= 3
     1740683.273      246991.975     1741170.086      246775.824
     1741626.391      246572.350
#Sta/Elev= 30
       0 1243.27    24.8 1236.38    65.9 1224.46   188.2 1194.27   269.2 1172.56
   288.1 1167.17   314.2 1158.84   332.2 1152.03   386.1 1129.33   416.7 1115.68
   422.1 1113.47   429.7 1111.30   476.1 1105.09   507.6 1101.43   520.6 1099.59
   525.1 1099.29   532.6 1098.87   540.1 1098.89   650.6 1100.87   663.6 1102.30
   683.6 1108.44   728.6 1123.77   754.6 1129.80   793.6 1142.45   813.7 1148.23
   853.7 1158.93   889.7 1168.04   936.6 1179.02   997.6 1193.92  1032.3 1201.62
#Mann= 3 , 0 , 0
       0     0.1       0   525.1   0.045       0   540.1     0.1       0
Bank Sta=   525.1,   540.1
Exp/Cntr=0.3,0.1

Type RM Length L Ch R = 1 ,9509,327.406,324.566,322.756
XS GIS Cut Line= 3
     1740660.688      247198.020     1741179.994      247219.616
     1741721.946      247202.270
#Sta/Elev= 30
       0 1210.48    11.6 1209.35    27.0 1207.09   106.7 1193.93   225.4 1170.35
   344.4 1141.39   374.2 1133.76   403.8 1125.46   415.7 1121.90   427.5 1117.38
   451.3 1104.51   463.2 1100.63   475.1 1098.67   517.8 1094.60   522.7 1094.07
   532.8 1094.42   558.2 1095.92   593.9 1095.94   617.6 1096.52   641.4 1098.41
   653.3 1099.96   665.1 1102.64   831.4 1151.58   856.5 1158.07   914.6 1170.10
   937.1 1173.59   983.2 1179.39  1029.2 1186.57  1045.3 1189.83  1062.0 1194.27
#Mann= 3 , 0 , 0
       0     0.1       0   517.8   0.045       0   532.8     0.1       0
Bank Sta=   517.8,   532.8
Exp/Cntr=0.3,0.1

Type RM Length L Ch R = 1 ,9184.4,368.161,358.021,346.307
XS GIS Cut Line= 3
     1740743.872      247522.652     1741366.284      247448.735
     1741852.272      247386.062
#Sta/Elev= 30
       0 1167.98    23.6 1166.87   119.2 1160.09   202.9 1150.35   226.8 1147.13
   286.6 1137.89   346.4 1127.24   358.2 1124.55   394.2 1112.98   411.6 1108.29
   442.0 1101.83   477.9 1096.89   489.9 1095.41   501.8 1094.66   589.2 1092.59
   618.4 1091.45   621.4 1091.37   633.4 1092.45   657.2 1101.96   710.2 1120.02
   753.1 1131.04   872.8 1164.44   884.7 1167.33   908.7 1171.38   956.6 1177.11
   992.5 1182.92  1028.5 1191.44  1076.3 1201.37  1091.9 1205.41  1116.8 1212.95
#Mann= 3 , 0 , 0
       0     0.1       0   618.4   0.045       0   633.4     0.1       0
Bank Sta=   618.4,   633.4
Exp/Cntr=0.3,0.1

Type RM Length L Ch R = 1 ,8826.4,400.064,400,405.144
XS GIS Cut Line= 3
     1741060.191      248033.195     1741492.405      247758.532
     1741896.169      247456.397
#Sta/Elev= 30
       0 1110.80    32.8 1107.95    78.5 1103.53   173.4 1098.47   215.6 1097.15
   282.8 1097.66   300.1 1097.04   328.2 1095.60   398.5 1091.08   429.0 1090.03
   497.0 1086.19   504.6 1085.97   506.4 1085.92   519.6 1086.60   525.8 1087.42
   540.7 1090.72   555.5 1095.11   570.3 1100.26   599.5 1111.17   619.3 1117.97
   674.1 1134.68   688.9 1138.69   718.4 1145.67   744.0 1151.38   862.7 1175.55
   896.5 1182.04   955.9 1192.55   970.7 1195.90   985.5 1200.22  1016.4 1211.11
#Mann= 3 , 0 , 0
       0     0.1       0   504.6   0.045       0   519.6     0.1       0
Bank Sta=   504.6,   519.6
Exp/Cntr=0.3,0.1

Type RM Length L Ch R = 1 ,8426.4,401.884,400,393.59
XS GIS Cut Line= 3
     1741214.249      248378.863     1741630.414      248106.223
     1742100.863      247890.889
#Sta/Elev= 30
       0 1195.79    14.3 1192.58    25.8 1189.27    36.0 1185.81    61.8 1175.25
    76.0 1170.19    85.9 1167.68   147.0 1155.65   163.1 1153.87   197.4 1152.03
   214.5 1149.12   300.3 1128.90   388.3 1105.31   416.6 1096.75   437.5 1091.03
   445.0 1089.56   469.3 1086.43     490 1082.28   501.5 1081.64     505 1081.73
   566.7 1085.41   619.0 1093.50   660.0 1100.71   717.1 1112.86   749.5 1120.43
   802.7 1131.60   828.9 1136.11   873.3 1141.42   945.3 1147.12  1014.9 1154.58
#Mann= 3 , 0 , 0
       0     0.1       0     490   0.045       0     505     0.1       0
Bank Sta=     490,     505
Exp/Cntr=0.3,0.1

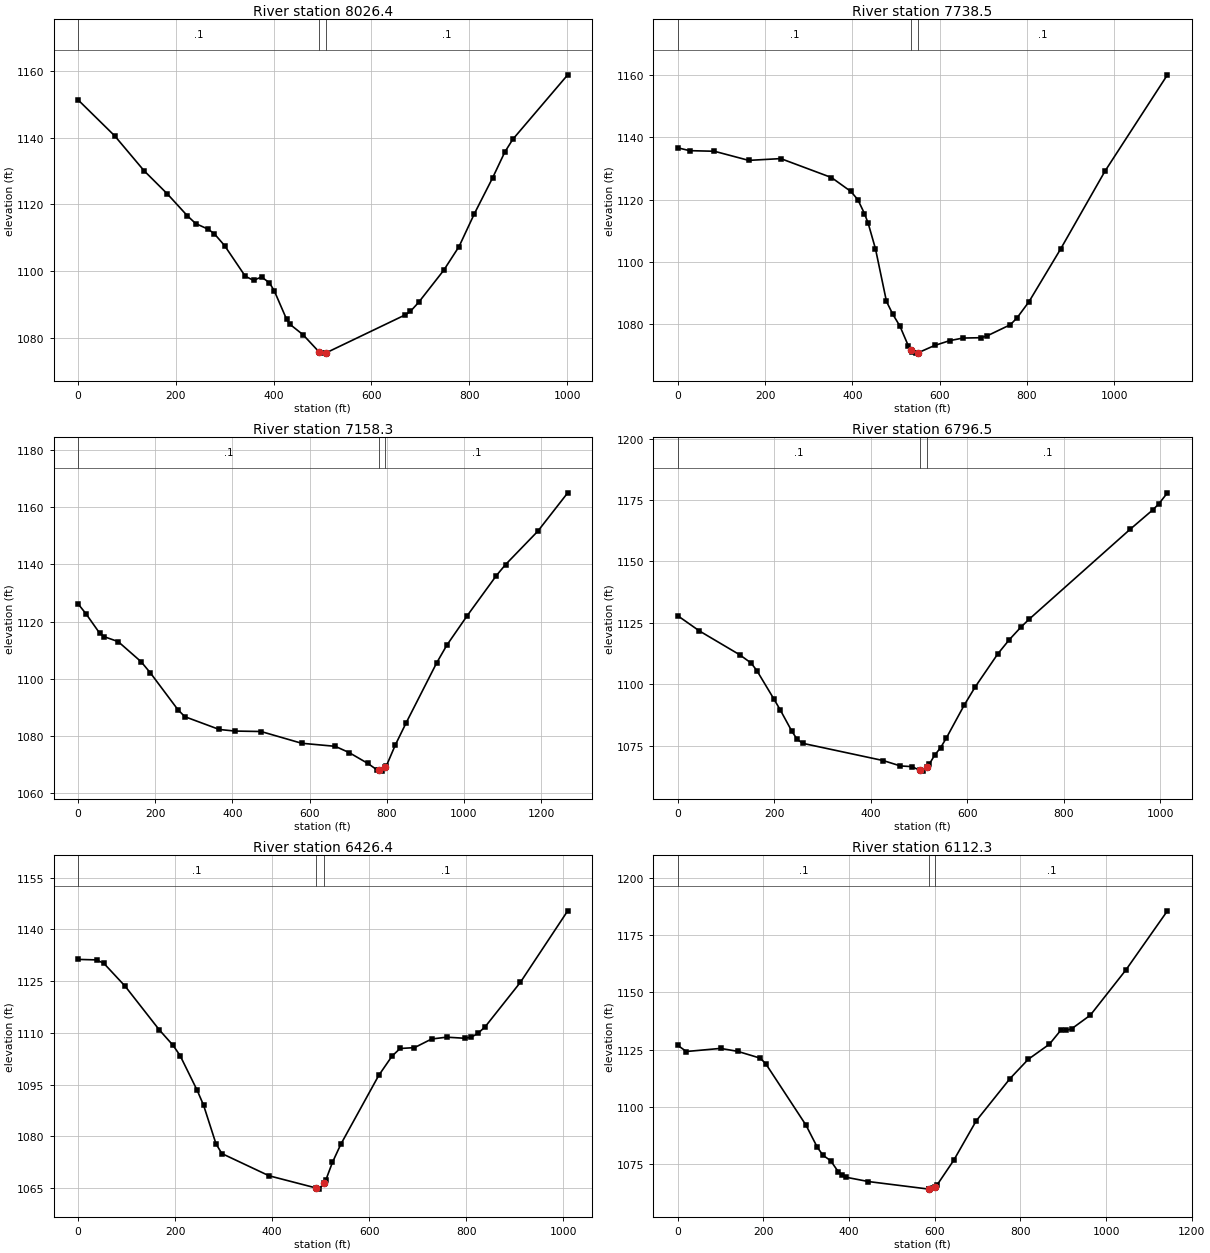
Type RM Length L Ch R = 1 ,8026.4,291.695,287.904,283.389
XS GIS Cut Line= 3
     1741491.922      248720.899     1741886.188      248412.635
     1742265.109      248085.024
#Sta/Elev= 30
       0 1151.37    74.9 1140.58   135.1 1130.09   182.5 1123.17   223.6 1116.58
   240.6 1114.25   265.9 1112.57   278.9 1111.17   299.7 1107.64   342.0 1098.45
   358.9 1097.21   375.3 1098.23   391.3 1096.49   401.2 1094.11   426.6 1085.51
   433.1 1084.06   460.4 1080.87     493 1075.73   496.8 1075.38     508 1075.52
   669.3 1086.87   679.5 1087.88   696.3 1090.57   747.8 1100.23   779.2 1107.36
   810.6 1117.23   847.8 1127.96   872.7 1135.69   889.1 1139.53  1001.4 1158.87
#Mann= 3 , 0 , 0
       0     0.1       0     493   0.045       0     508     0.1       0
Bank Sta=     493,     508
Exp/Cntr=0.3,0.1

Type RM Length L Ch R = 1 ,7738.5,594.987,580.224,549.418
XS GIS Cut Line= 3
     1741702.485      249032.256     1742077.516      248620.835
     1742363.112      248132.678
#Sta/Elev= 30
       0 1136.64    27.2 1135.72    83.9 1135.53   162.7 1132.60   236.1 1133.17
   352.3 1127.09   396.7 1122.63   412.8 1119.97   428.0 1115.50   436.4 1112.42
   453.2 1104.18   478.4 1087.29   493.1 1083.13   509.2 1079.38   528.8 1072.94
   535.1 1071.58   537.2 1071.08   545.6 1070.71   550.1 1070.78   588.7 1073.17
   623.4 1074.72   653.5 1075.55   694.8 1075.66   708.6 1076.22   762.2 1079.83
   777.3 1081.98   804.9 1087.20   877.5 1104.15   979.2 1129.15  1122.3 1160.07
#Mann= 3 , 0 , 0
       0     0.1       0   535.1   0.045       0   550.1     0.1       0
Bank Sta=   535.1,   550.1
Exp/Cntr=0.3,0.1

Type RM Length L Ch R = 1 ,7158.3,366.491,361.749,358.879
XS GIS Cut Line= 4
     1742396.846      249448.310     1742371.543      249110.532
     1742440.376      248667.241     1742477.061      248186.758
#Sta/Elev= 30
       0 1126.20    20.7 1122.70    56.4 1115.86    68.3 1114.67   104.0 1112.98
   163.5 1105.94   187.4 1102.05   258.8 1089.17   276.8 1086.71   366.2 1082.23
   406.7 1081.68   474.3 1081.52   579.6 1077.41   666.6 1076.34   702.6 1074.15
   750.7 1070.39   774.7 1068.13   780.9 1067.90   786.7 1067.66   795.9 1068.93
   798.6 1069.31   822.4 1076.82   850.1 1084.47   929.6 1105.55   955.9 1111.73
  1008.9 1122.08  1084.4 1136.10  1108.2 1139.95  1191.6 1151.59  1269.2 1165.03
#Mann= 3 , 0 , 0
       0     0.1       0   780.9   0.045       0   795.9     0.1       0
Bank Sta=   780.9,   795.9
Exp/Cntr=0.3,0.1

Type RM Length L Ch R = 1 ,6796.5,355.307,370.123,382.86
XS GIS Cut Line= 3
     1742811.710      249282.582     1742779.854      248784.249
     1742754.942      248269.661
#Sta/Elev= 30
       0 1127.92    44.9 1121.73   128.2 1112.06   152.0 1108.68   163.9 1105.60
   199.6 1093.92   212.2 1089.67   236.2 1081.01   247.2 1077.69   259.1 1076.02
   425.6 1069.02   461.3 1066.83   485.1 1066.55   501.6 1065.04   508.9 1064.72
   516.6 1066.42   520.8 1067.48   532.7 1071.33   544.6 1074.27   556.5 1078.20
   593.6 1091.61   616.3 1098.99   663.4 1112.51   687.2 1118.25   711.0 1123.29
   727.8 1126.48   936.8 1163.01   984.4 1171.02   996.3 1173.35  1014.5 1177.91
#Mann= 3 , 0 , 0
       0     0.1       0   501.6   0.045       0   516.6     0.1       0
Bank Sta=   501.6,   516.6
Exp/Cntr=0.3,0.1

Type RM Length L Ch R = 1 ,6426.4,317.031,314.113,312.775
XS GIS Cut Line= 3
     1742814.291      249352.520     1743093.924      248939.554
     1743344.024      248494.511
#Sta/Elev= 30
       0 1131.28    38.3 1131.14    53.5 1130.10    97.1 1123.51   167.3 1110.89
   196.0 1106.35   210.3 1103.42   245.4 1093.38   258.7 1089.04   284.3 1077.84
   296.4 1075.01   393.6 1068.57   491.2 1065.01   497.1 1064.70   506.2 1066.39
   510.8 1067.37   524.2 1072.42   541.6 1077.71   619.7 1097.65   647.0 1103.23
   663.7 1105.46   693.4 1105.71   728.7 1108.21   759.6 1108.74   796.8 1108.43
   810.4 1108.75   824.0 1109.83   838.9 1111.73   911.6 1124.63  1009.2 1145.36
#Mann= 3 , 0 , 0
       0     0.1       0   491.2   0.045       0   506.2     0.1       0
Bank Sta=   491.2,   506.2
Exp/Cntr=0.3,0.1

Type RM Length L Ch R = 1 ,6112.3,397.358,386.817,376.263
XS GIS Cut Line= 3
     1743108.074      249600.114     1743378.676      249061.682
     1743611.020      248573.471
#Sta/Elev= 30
       0 1126.87    20.2 1124.18   100.0 1125.54   139.8 1124.26   193.0 1121.25
   206.3 1118.59   299.3 1092.00   325.8 1082.31   339.1 1078.80   357.0 1076.42
   374.6 1071.65   383.5 1069.96   392.3 1069.21   445.3 1067.30   586.1 1064.00
   586.9 1063.99   595.7 1064.32   601.1 1065.10   604.9 1065.65   644.3 1076.59
   696.9 1093.88   775.8 1112.35   818.4 1120.78   867.8 1127.39   894.1 1133.44
   907.3 1133.42   920.4 1134.22   963.2 1140.06  1046.1 1159.80  1143.3 1185.71
#Mann= 3 , 0 , 0
       0     0.1       0   586.1   0.045       0   601.1     0.1       0
Bank Sta=   586.1,   601.1
Exp/Cntr=0.3,0.1

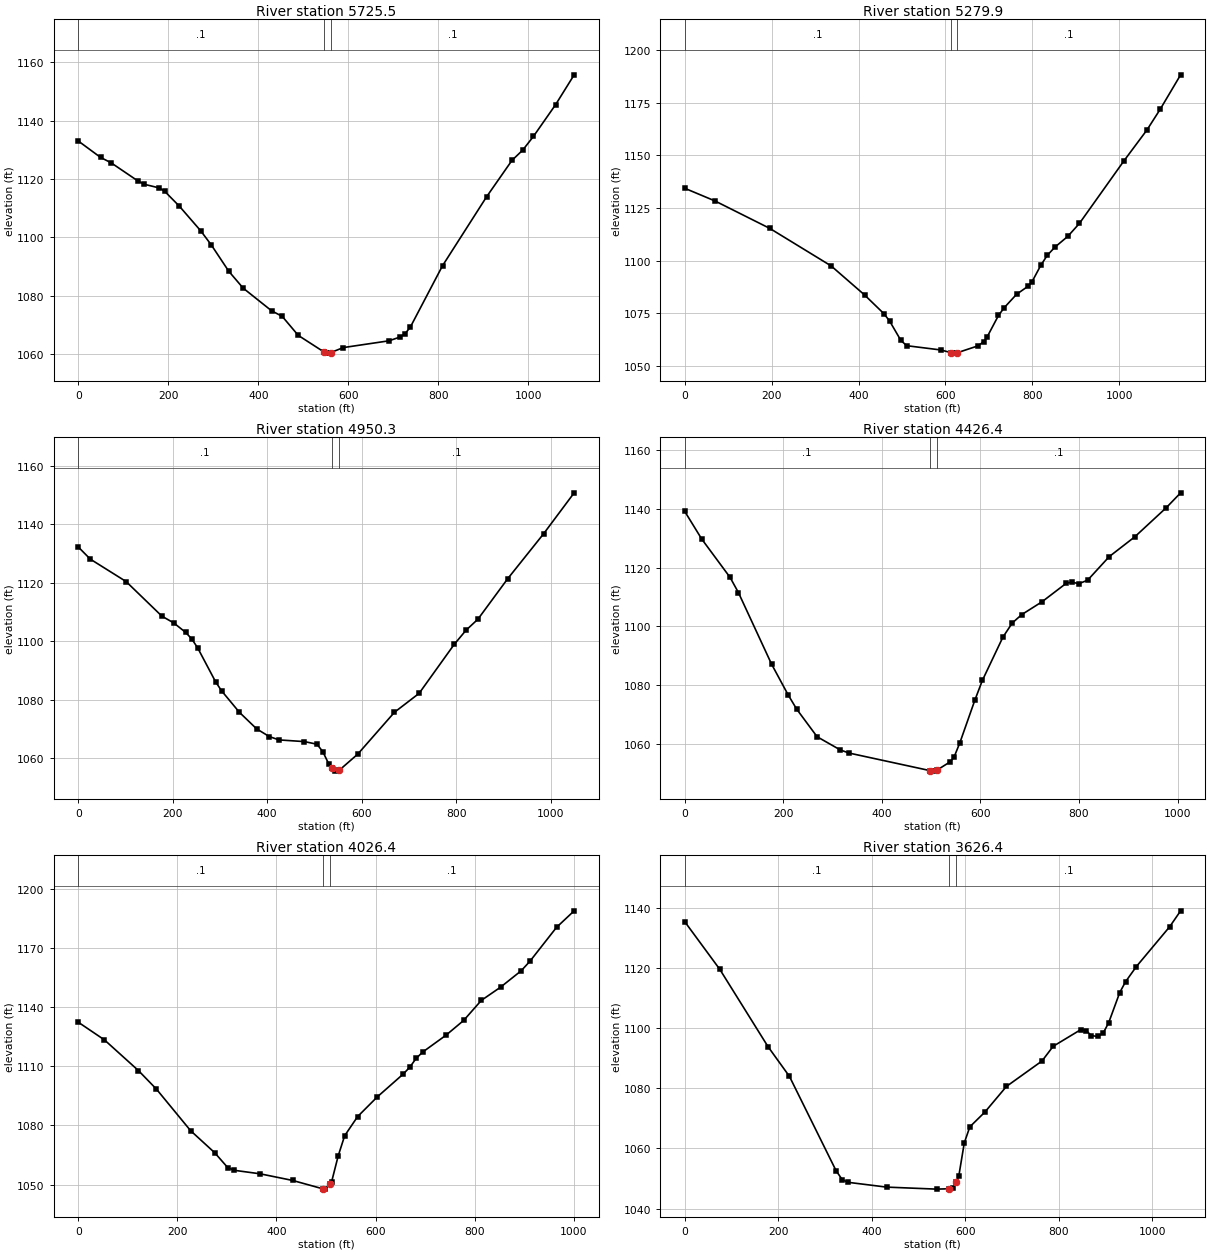
Type RM Length L Ch R = 1 ,5725.5,418.703,445.558,457.41
XS GIS Cut Line= 3
     1743639.387      249785.652     1743635.366      249211.841
     1743638.920      248684.148
#Sta/Elev= 30
       0 1132.96    49.3 1127.36    73.0 1125.48   132.4 1119.27   146.4 1118.14
   179.9 1116.88   191.7 1115.75   224.7 1110.58   271.9 1102.18   295.4 1097.34
   334.2 1088.32   366.2 1082.53   429.2 1074.78   453.0 1072.84   488.6 1066.33
     546 1060.62   554.8 1060.25     561 1060.46   588.6 1062.15   690.4 1064.48
   714.2 1065.75   726.0 1066.90   737.9 1069.27   809.1 1090.22   907.0 1113.86
   963.5 1126.36   987.2 1129.85  1011.0 1134.54  1060.3 1145.44  1101.5 1155.66
#Mann= 3 , 0 , 0
       0     0.1       0     546   0.045       0     561     0.1       0
Bank Sta=     546,     561
Exp/Cntr=0.3,0.1

Type RM Length L Ch R = 1 ,5279.9,321.127,329.563,312.227
XS GIS Cut Line= 3
     1743701.233      249782.841     1743967.908      249217.764
     1744201.623      248756.760
#Sta/Elev= 30
       0 1134.31    69.5 1128.30   195.8 1115.25   337.1 1097.42   414.0 1083.63
   458.4 1074.76   471.5 1071.29   497.5 1062.06   510.9 1059.54   589.6 1057.51
   612.6 1056.27   622.5 1056.01   627.6 1056.21   675.5 1059.49   688.4 1061.50
   695.6 1063.48   722.3 1073.91   735.6 1077.61   763.9 1083.95   790.4 1087.78
   799.2 1089.79   819.7 1097.71   834.5 1102.43   852.2 1106.34   882.0 1111.50
   908.6 1117.61  1011.2 1147.35  1064.2 1162.03  1095.0 1171.96  1141.7 1188.21
#Mann= 3 , 0 , 0
       0     0.1       0   612.6   0.045       0   627.6     0.1       0
Bank Sta=   612.6,   627.6
Exp/Cntr=0.3,0.1

Type RM Length L Ch R = 1 ,4950.3,515.176,523.949,530.969
XS GIS Cut Line= 3
     1743939.151      249902.683     1744133.473      249367.000
     1744296.472      248915.438
#Sta/Elev= 30
       0 1132.28    25.3 1128.15   101.1 1120.48   176.9 1108.64   202.5 1106.27
   227.4 1103.05   240.1 1100.86   252.7 1097.77   290.6 1086.19   303.2 1083.11
   341.1 1075.73   377.5 1070.08   404.2 1067.45   424.9 1066.29   478.9 1065.71
   505.3 1064.82   517.6 1062.29   530.5 1058.00   537.4 1056.80   543.2 1055.61
   552.4 1055.90   591.8 1061.45   669.4 1075.75   721.6 1082.22   795.8 1098.95
   820.9 1103.81   846.1 1107.59   909.2 1121.45   985.0 1136.78  1049.9 1150.83
#Mann= 3 , 0 , 0
       0     0.1       0   537.4   0.045       0   552.4     0.1       0
Bank Sta=   537.4,   552.4
Exp/Cntr=0.3,0.1

Type RM Length L Ch R = 1 ,4426.4,390.944,400,410.536
XS GIS Cut Line= 3
     1744106.053      250070.614     1744443.312      249695.582
     1744754.898      249302.232
#Sta/Elev= 30
       0 1139.10    34.4 1129.71    91.9 1116.67   108.8 1111.52   176.0 1087.19
   209.6 1076.74   227.0 1071.86   268.5 1062.46   315.8 1057.95   333.6 1056.90
   496.9 1050.96   503.9 1050.76   511.9 1051.12   537.7 1053.84   546.1 1055.40
   558.3 1060.46   588.6 1074.89   603.8 1081.60   645.5 1096.33   664.6 1101.17
   683.7 1104.01   725.0 1108.39   774.3 1114.70   785.5 1115.07   799.7 1114.52
   817.6 1115.75   861.3 1123.74   913.2 1130.48   977.2 1140.41  1006.2 1145.45
#Mann= 3 , 0 , 0
       0     0.1       0   496.9   0.045       0   511.9     0.1       0
Bank Sta=   496.9,   511.9
Exp/Cntr=0.3,0.1

Type RM Length L Ch R = 1 ,4026.4,388.981,400,409.304
XS GIS Cut Line= 3
     1744198.261      250236.142     1744651.578      250023.995
     1745104.890      249811.850
#Sta/Elev= 30
       0 1132.40    52.7 1123.45   121.4 1107.85   157.6 1098.46   226.7 1077.33
   275.5 1066.09   301.7 1058.56   314.9 1057.21   366.8 1055.44   432.8 1052.05
     493 1047.85   498.4 1047.65     508 1050.03   511.5 1051.52   524.6 1064.51
   537.7 1074.78   563.9 1084.51   603.2 1094.41   655.7 1106.05   668.8 1109.48
   681.9 1114.01   695.0 1117.23   742.2 1125.81   777.9 1133.32   813.6 1143.51
   852.3 1150.20   894.0 1158.54   911.8 1163.41   965.4 1180.60  1001.0 1189.00
#Mann= 3 , 0 , 0
       0     0.1       0     493   0.045       0     508     0.1       0
Bank Sta=     493,     508
Exp/Cntr=0.3,0.1

Type RM Length L Ch R = 1 ,3626.4,413.304,398.417,385.245
XS GIS Cut Line= 3
     1744242.206      250361.397     1744814.788      250387.961
     1745302.243      250373.459
#Sta/Elev= 30
       0 1135.31    75.1 1119.44   178.0 1093.81   223.9 1083.91   323.6 1052.59
   336.6 1049.64   348.5 1048.72   431.7 1047.11   538.6 1046.44   565.7 1046.56
   574.3 1046.68   580.7 1048.90   586.2 1050.72   598.0 1061.81   609.9 1067.15
   642.1 1072.05   688.2 1080.57   764.3 1089.03   788.1 1093.90   847.5 1099.47
   859.3 1099.09   869.6 1097.48   883.1 1097.18   895.0 1098.27   906.9 1101.72
   930.6 1111.77   943.0 1115.36   966.2 1120.42  1037.5 1133.66  1060.9 1138.94
#Mann= 3 , 0 , 0
       0     0.1       0   565.7   0.045       0   580.7     0.1       0
Bank Sta=   565.7,   580.7
Exp/Cntr=0.3,0.1

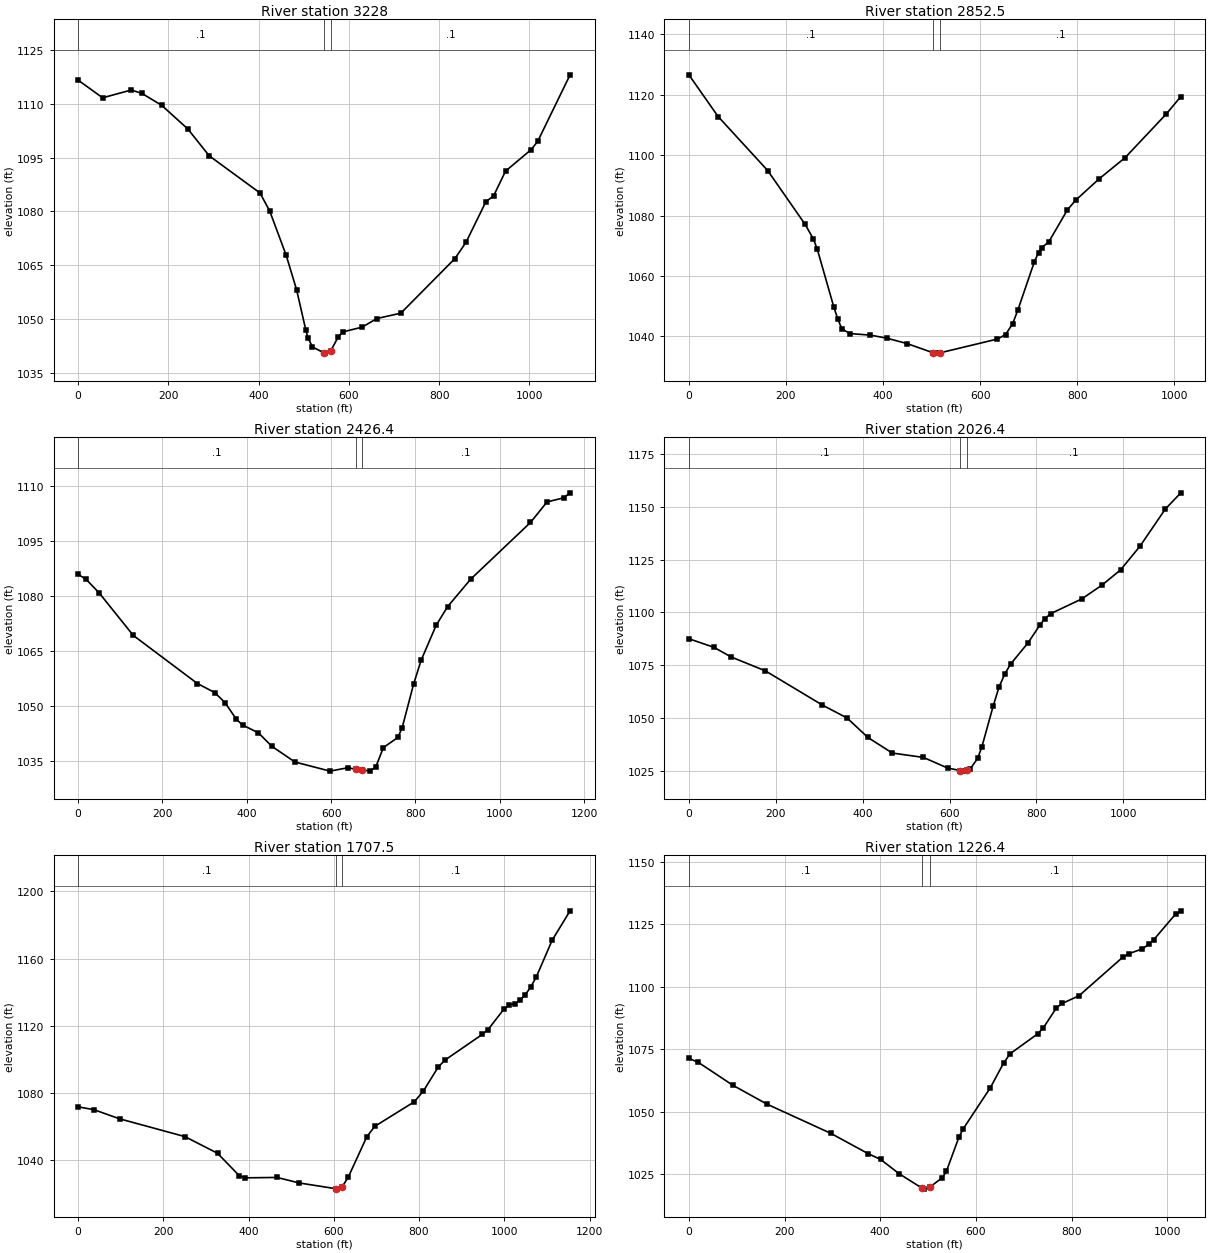
Type RM Length L Ch R = 1 ,3228,380.503,375.428,373.03
XS GIS Cut Line= 3
     1744308.448      251019.760     1744733.517      250720.059
     1745208.026      250404.111
#Sta/Elev= 30
       0 1116.66    54.3 1111.73   117.9 1113.91   141.5 1112.94   185.1 1109.63
   243.2 1103.01   290.4 1095.54   403.0 1085.16   424.6 1080.10   461.1 1067.75
   484.2 1058.10   504.6 1046.85   509.8 1044.61   519.2 1042.19     545 1040.50
   547.7 1040.45     560 1041.13   576.2 1044.94   586.8 1046.38   629.6 1047.71
   661.8 1050.10   715.2 1051.61   835.1 1066.86   859.7 1071.42   903.6 1082.72
   920.7 1084.35   947.1 1091.25  1004.2 1097.29  1018.4 1099.57  1090.2 1118.14
#Mann= 3 , 0 , 0
       0     0.1       0     545   0.045       0     560     0.1       0
Bank Sta=     545,     560
Exp/Cntr=0.3,0.1

Type RM Length L Ch R = 1 ,2852.5,431.489,426.155,415.823
XS GIS Cut Line= 3
     1744655.019      251303.394     1745014.903      250934.726
     1745413.596      250636.084
#Sta/Elev= 30
       0 1126.59    60.3 1112.77   162.3 1094.90   239.6 1077.04   256.3 1072.27
   264.3 1068.95   298.3 1049.85   306.7 1045.71   315.2 1042.46   331.6 1040.91
   373.9 1040.39   407.5 1039.39   449.5 1037.59   502.2 1034.59   508.2 1034.43
   517.2 1034.52   635.4 1039.09   652.2 1040.56   667.0 1044.20   677.8 1048.77
   711.5 1064.63   720.2 1067.72   726.4 1069.35   741.2 1071.22   779.6 1081.85
   796.5 1085.03   845.0 1092.14   898.3 1099.12   983.1 1113.58  1013.3 1119.39
#Mann= 3 , 0 , 0
       0     0.1       0   502.2   0.045       0   517.2     0.1       0
Bank Sta=   502.2,   517.2
Exp/Cntr=0.3,0.1

Type RM Length L Ch R = 1 ,2426.4,403.508,400,399.164
XS GIS Cut Line= 4
     1744915.663      251702.876     1745136.357      251526.070
     1745333.445      251196.713     1745544.819      250743.567
#Sta/Elev= 30
       0 1085.83    18.8 1084.49    50.0 1080.76   130.7 1069.22   282.8 1056.12
   323.9 1053.66   348.4 1050.90   375.4 1046.37   389.9 1044.83   427.7 1042.69
   459.1 1039.06   514.1 1034.76   597.4 1032.28   638.9 1033.19   659.1 1032.80
   674.1 1032.54   692.8 1032.33   706.0 1033.45   723.8 1038.69   758.3 1041.45
   768.5 1044.14   795.3 1055.87   813.2 1062.41   848.9 1071.94   876.2 1077.05
   930.8 1084.51  1072.7 1099.95  1112.0 1105.55  1151.3 1106.65  1166.6 1108.02
#Mann= 3 , 0 , 0
       0     0.1       0   659.1   0.045       0   674.1     0.1       0
Bank Sta=   659.1,   674.1
Exp/Cntr=0.3,0.1

Type RM Length L Ch R = 1 ,2026.4,321.334,318.881,310.379
XS GIS Cut Line= 3
     1745421.675      251902.470     1745689.180      251329.442
     1745907.184      250879.681
#Sta/Elev= 30
       0 1087.52    57.3 1083.47    97.5 1078.86   176.1 1072.28   307.4 1056.05
   364.2 1049.92   412.0 1040.70   468.2 1033.31   539.7 1031.24   595.4 1026.22
   624.9 1025.00   634.8 1024.74   639.9 1025.04   647.9 1025.87   664.6 1030.80
   674.3 1036.21   700.7 1055.85   713.9 1064.67   727.1 1070.83   740.3 1075.46
   780.6 1085.57   807.8 1093.98   819.5 1097.07   833.4 1099.48   904.5 1106.42
   951.4 1113.04   993.4 1120.14  1037.8 1131.26  1096.5 1148.99  1132.2 1156.70
#Mann= 3 , 0 , 0
       0     0.1       0   624.9   0.045       0   639.9     0.1       0
Bank Sta=   624.9,   639.9
Exp/Cntr=0.3,0.1

Type RM Length L Ch R = 1 ,1707.5,463.638,481.119,496.104
XS GIS Cut Line= 3
     1745736.990      251987.588     1745979.840      251374.608
     1746144.766      250907.788
#Sta/Elev= 30
       0 1071.78    36.9 1070.10    97.2 1064.66   250.5 1054.07   327.1 1044.15
   378.2 1030.79   390.9 1029.53   466.8 1029.77   518.6 1026.50   604.2 1023.10
   608.0 1022.82   619.2 1024.08   633.6 1029.81   677.4 1053.97   696.0 1060.16
   789.1 1074.82   810.2 1081.20   844.9 1095.44   860.6 1099.55   948.7 1114.94
   961.3 1117.57   999.1 1129.89  1011.7 1132.29  1024.3 1133.15  1036.9 1135.13
  1049.5 1138.59  1062.1 1143.10  1074.7 1148.83  1112.4 1170.95  1154.4 1188.40
#Mann= 3 , 0 , 0
       0     0.1       0   604.2   0.045       0   619.2     0.1       0
Bank Sta=   604.2,   619.2
Exp/Cntr=0.3,0.1

Type RM Length L Ch R = 1 ,1226.4,406.735,400,391.704
XS GIS Cut Line= 3
     1745769.252      251986.833     1746220.052      251780.794
     1746677.465      251507.779
#Sta/Elev= 30
       0 1071.32    20.1 1069.65    91.8 1060.56   163.5 1052.97   296.3 1041.35
   374.6 1033.21   400.7 1030.89   439.9 1025.11   488.2 1019.31   492.1 1019.01
   503.2 1019.78   529.6 1023.53   538.3 1026.15   564.3 1039.68   572.9 1042.96
   630.2 1059.56   657.8 1069.41   671.7 1073.18   728.8 1081.05   740.8 1083.47
   768.4 1091.51   780.7 1093.29   815.4 1096.32   906.7 1111.70   920.5 1113.21
   948.2 1115.10   962.0 1117.02   971.2 1118.63  1017.3 1128.98  1028.3 1130.29
#Mann= 3 , 0 , 0
       0     0.1       0   488.2   0.045       0   503.2     0.1       0
Bank Sta=   488.2,   503.2
Exp/Cntr=0.3,0.1

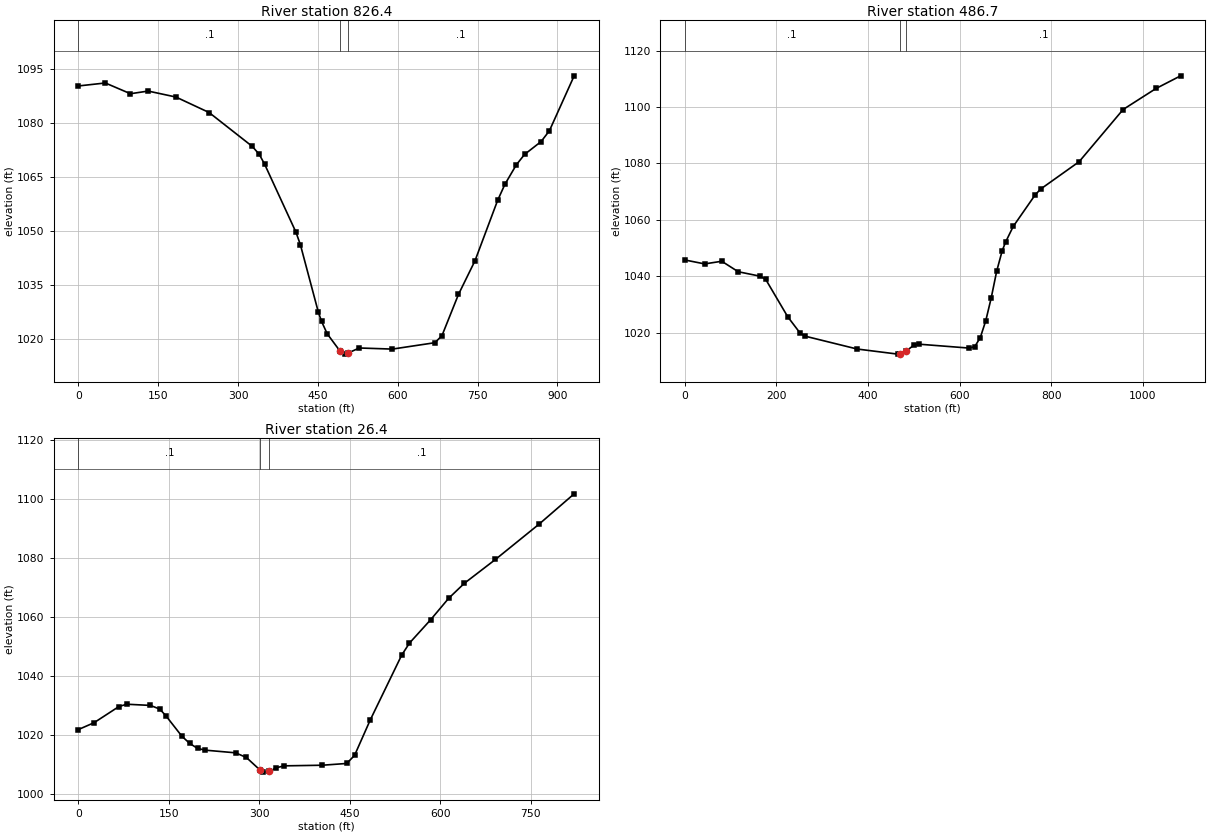
Type RM Length L Ch R = 1 ,826.4,356.314,339.739,327.365
XS GIS Cut Line= 3
     1746037.324      252414.105     1746402.263      252073.243
     1746681.084      251742.233
#Sta/Elev= 30
       0 1090.28    50.7 1091.11    97.9 1088.12   131.1 1088.86   183.3 1087.20
   245.6 1082.89   326.9 1073.44   339.8 1071.25   349.9 1068.51   408.7 1049.61
   417.1 1046.10   450.7 1027.40   456.8 1024.77   467.5 1021.31   491.9 1016.43
   501.1 1015.66   506.9 1015.98   527.7 1017.37   589.8 1017.06   669.7 1018.84
   683.0 1020.80   714.0 1032.27   745.1 1041.66   787.6 1058.46   801.3 1062.93
   822.7 1068.34   838.1 1071.22   869.2 1074.81   884.8 1077.81   931.3 1093.10
#Mann= 3 , 0 , 0
       0     0.1       0   491.9   0.045       0   506.9     0.1       0
Bank Sta=   491.9,   506.9
Exp/Cntr=0.3,0.1

Type RM Length L Ch R = 1 ,486.7,471.078,460.261,447.911
XS GIS Cut Line= 3
     1746638.916      252641.810     1746713.403      252159.848
     1746797.392      251571.011
#Sta/Elev= 30
       0 1045.78    43.3 1044.38    80.7 1045.32   116.7 1041.60   164.8 1040.01
   176.8 1038.85   224.8 1025.61   251.5 1019.90   261.9 1018.78   376.3 1014.19
   465.1 1012.38     469 1012.45     484 1013.55   501.3 1015.71   511.8 1015.90
   621.1 1014.52   633.1 1015.07   645.1 1018.23   657.0 1024.18   668.8 1032.19
   681.0 1041.86   693.0 1049.08   700.7 1052.24   717.0 1057.66   765.0 1068.88
   777.0 1070.94   860.9 1080.63   956.9 1099.14  1028.8 1106.60  1082.5 1111.09
#Mann= 3 , 0 , 0
       0     0.1       0     469   0.045       0     484     0.1       0
Bank Sta=     469,     484
Exp/Cntr=0.3,0.1

Type RM Length L Ch R = 1 ,26.4,28.967,26.391,23.688
XS GIS Cut Line= 3
     1747201.152      252385.993     1747073.452      252104.482
     1746863.810      251635.408
#Sta/Elev= 30
       0 1021.80    26.0 1024.12    67.4 1029.63    80.4 1030.40   119.5 1030.00
   135.2 1028.74   145.6 1026.38   171.7 1019.55   184.7 1017.10   197.8 1015.40
   210.8 1014.81   260.8 1013.91   278.7 1012.33   301.6 1008.02   305.6 1007.36
   316.6 1007.58   328.1 1008.82   341.1 1009.49   404.5 1009.70   445.1 1010.30
   458.1 1013.04   484.1 1025.05   536.2 1047.04   549.2 1051.16   584.2 1059.05
   614.2 1066.35   640.2 1071.44   691.8 1079.54   764.0 1091.49   822.3 1101.80
#Mann= 3 , 0 , 0
       0     0.1       0   301.6   0.045       0   316.6     0.1       0
Bank Sta=   301.6,   316.6
Exp/Cntr=0.3,0.1